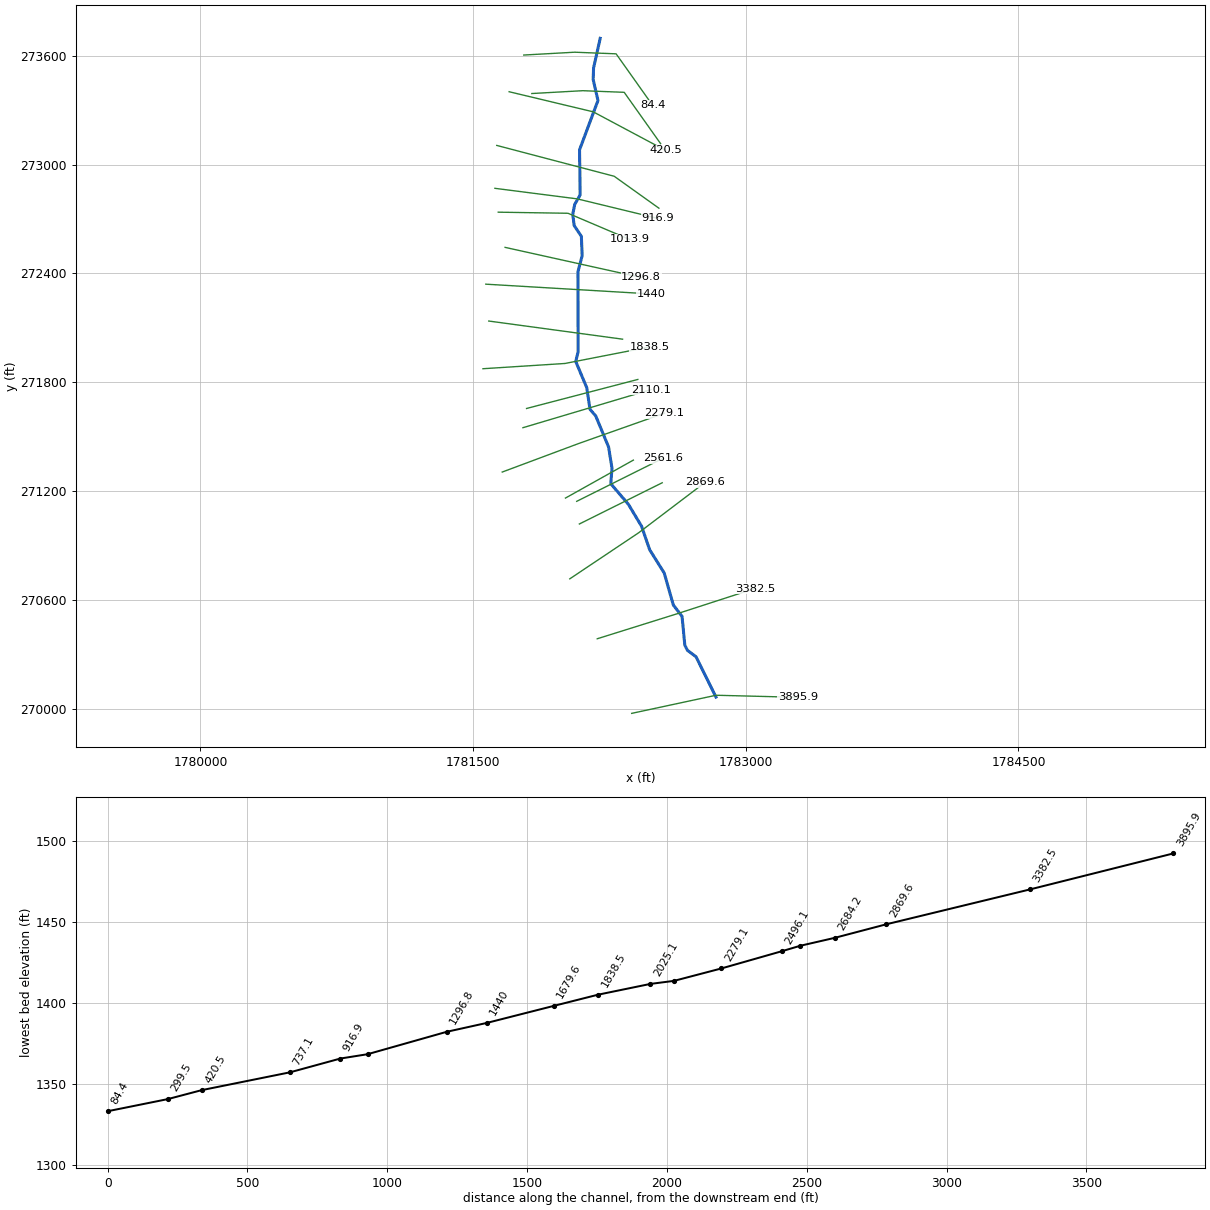
--- LonglickBr.prj (project) ---

Proj Title=LonglickBr
Current Plan=p01
Default Exp/Contr=0,0
English Units
Geom File=g01
Flow File=f01
Plan File=p01
BEGIN DESCRIPTION:
END DESCRIPTION:
DSS Export Rating Curves= 0
DSS Export Rating Curve Sorted= 0
DSS Export Volume Flow Curves= 0
DXF OffsetX= 0
DXF OffsetY= 0
DXF ScaleX= 0
DXF ScaleY= 0

--- LonglickBr.p01 (plan) ---

Plan Title=Floodplain
Program Version=4.00
Geom File=g01
Flow File=f01
K Sum by GR=0
Std Step Tol=0.01
Critical Tol=0.01
Num of Std Step Trials=20
Max Error Tol=0.3
Flow Tol Ratio=0.001
Split Flow NTrial=30
Split Flow Tol=0.02
Split Flow Ratio=0.02
Log Output Level=0
Friction Slope Method=1
Unsteady Friction Slope Method=2
Unsteady Bridges Friction Slope Method=1
Global Log Level=0
CheckData=False
Run HTab=0
Run UNet=0
Run PostProcess=0
UNET Theta=0
UNET Theta Warmup=0
UNET ZTol=0
UNET ZSATol=0
UNET MxIter=0
UNET MaxInSteps=0
UNET DtIC=0
UNET DtMin=0
UNET MaxCRTS=0
UNET WFStab=0
UNET SFStab=0
UNET WFX=0
UNET SFX=0
UNET DSS MLevel=0
UNET DZMax Abort=0
UNET Convert EG Bridges=0
UNET Use Existing IB Tables=0
UNET Froude Limit=0
UNET Froude Power=0
Write IC File=0
Echo Input=False
Echo Output=False
Write Detailed=0

--- LonglickBr.f01 (steady flow) ---

Flow Title=NFF Regression Equation
Program Version=4.00
Number of Profiles=1
Profile Names=P100yr
River Rch & RM=LonglickBr,Main      ,3895.9
568.6461
River Rch & RM=LonglickBr,Main      ,2561.6
607.5172
River Rch & RM=LonglickBr,Main      ,299.5
646.9036
Boundary for River Rch & Prof#=LonglickBr,Main      ,1
Up Type=0
Dn Type=3
Dn Slope=0.038453

--- LonglickBr.g01 (geometry) ---

Geom Title=USGS 10m DEM
Program Version=4.00

River Reach=LonglickBr      ,Main
Reach XY= 30
     1782836.011      270065.341     1782726.515      270287.212
     1782679.052      270323.111     1782664.742      270351.732
      1782649.33      270510.252     1782601.442      270572.728
     1782551.356      270749.133     1782470.995       270877.93
     1782426.962      271006.728     1782354.307      271127.819
     1782257.434      271241.205     1782264.039       271327.07
     1782245.325      271443.758     1782174.871      271614.387
     1782142.947      271651.815     1782125.334      271770.705
     1782064.788      271914.914     1782077.998      271969.956
     1782076.897      272410.289     1782100.015      272498.355
     1782095.611      272605.136     1782055.981      272664.581
     1782048.276      272727.329     1782059.284      272781.269
     1782089.006      272833.008     1782085.604      273081.405
      1782186.98      273353.702     1782160.561      273469.289
     1782162.762      273533.138     1782199.241      273696.226

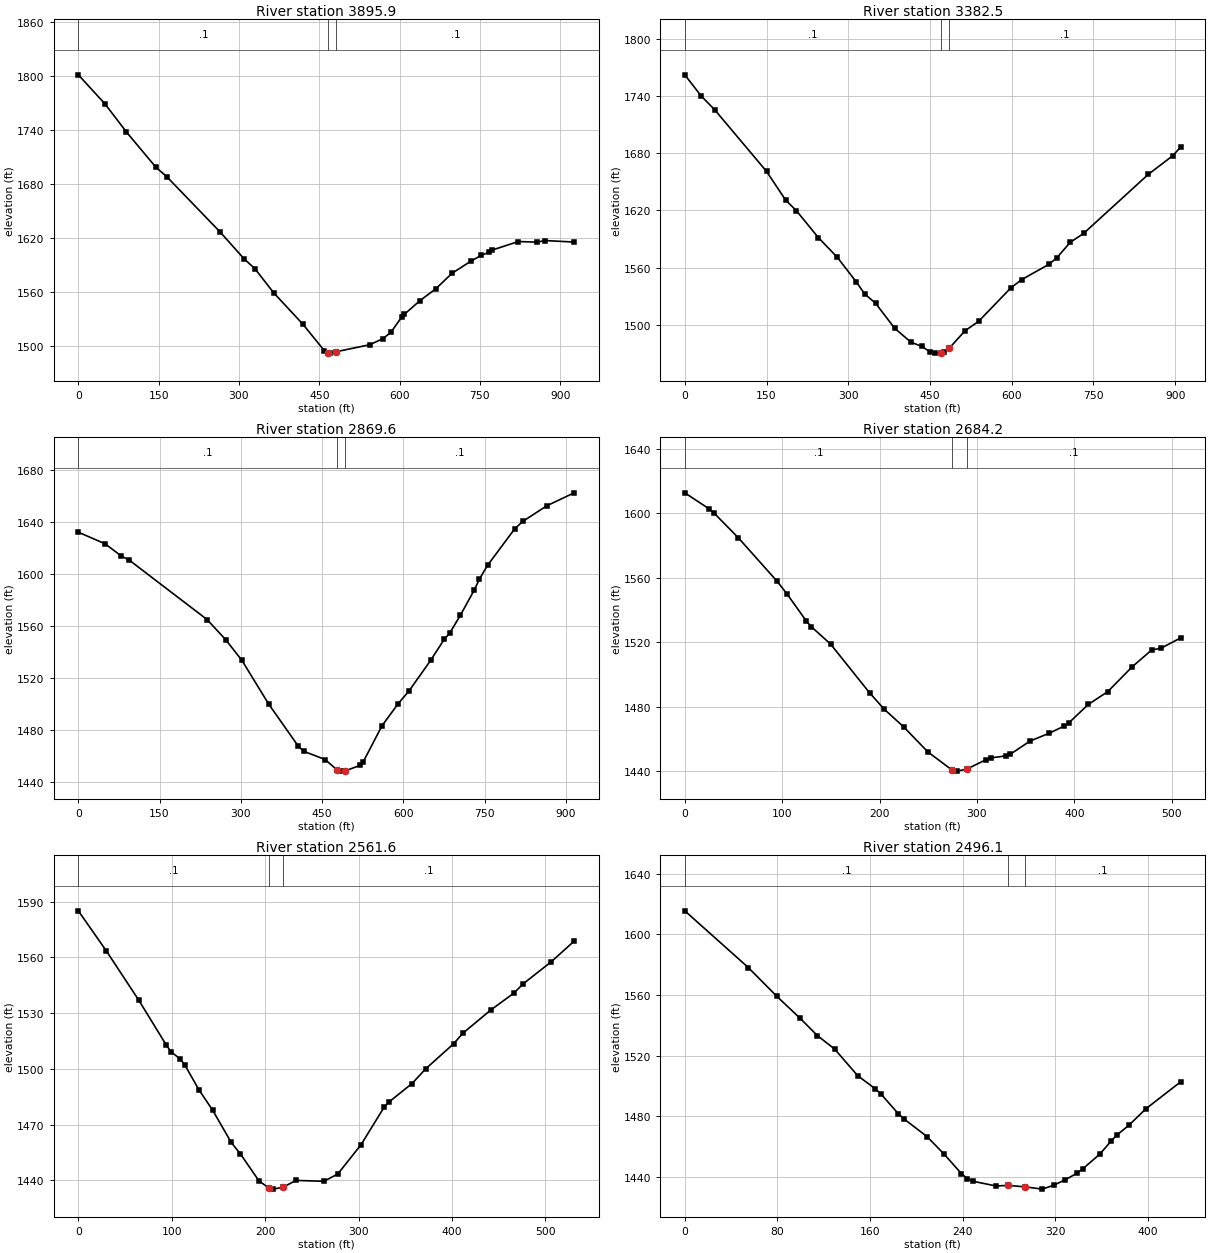
Type RM Length L Ch R = 1 ,3895.9  ,511.8,513.4,520.8
XS GIS Cut Line= 3
     1782372.457      269975.399     1782836.521      270075.328
     1783287.791       270063.83
#Sta/Elev= 30
       0 1801.69      50 1769.24    89.9 1738.09   144.9 1698.94   164.9 1688.64
   264.8 1627.02   309.8 1597.07   329.8 1586.21   364.8  1559.5   419.7 1524.32
   459.7 1494.95   467.2 1492.49   469.7 1492.38   482.2 1494.02   544.2 1501.68
     569 1508.49   583.8 1515.51   603.7  1532.2   608.6 1535.35   638.4 1550.85
   668.2 1564.13   697.9 1581.08   732.6 1594.36   752.5 1601.03   767.4 1604.51
   772.3 1606.78   821.9 1616.43   856.7  1615.7   871.6  1617.5   926.1 1615.82
#Mann= 3 , 0 , 0
       0      .1       0   467.2    .045       0   482.2      .1       0
Bank Sta=467.2,482.2
XS Rating Curve= 0 ,0
Exp/Cntr=0.3,0.1

Type RM Length L Ch R = 1 ,3382.5  ,505,512.9,526.8
XS GIS Cut Line= 3
     1782182.942      270386.669       1782617.1      270522.783
      1783049.84      270663.456
#Sta/Elev= 30
       0 1762.36      30 1740.22      55 1725.57     150 1660.98     185 1630.89
     205 1619.58     245  1591.5     280 1570.66     315 1544.72     330 1532.28
     350  1522.6     385 1496.31     415 1481.57     435 1477.17     450  1471.5
   459.9 1470.11   470.5 1470.51   474.8  1470.9   485.5 1475.34   514.4 1493.65
   539.1  1503.4   598.4 1538.63   618.2 1547.26   667.7 1563.19   682.5 1570.02
   707.2 1586.35     732 1595.84   850.7 1657.84   895.2 1677.28     910 1686.35
#Mann= 3 , 0 , 0
       0      .1       0   470.5    .045       0   485.5      .1       0
Bank Sta=470.5,485.5
XS Rating Curve= 0 ,0
Exp/Cntr=0.3,0.1

Type RM Length L Ch R = 1 ,2869.6  ,190,185.4,180.8
XS GIS Cut Line= 3
       1782031.9      270716.931     1782410.382      270970.617
     1782776.512      271248.848
#Sta/Elev= 30
       0 1632.29    49.5 1623.35    79.2 1614.01    94.1 1610.79   237.7 1565.14
   272.4  1549.5   302.1  1533.7   351.6 1500.07   406.1 1467.79     416 1463.89
   455.6 1457.53   477.6  1449.6   485.6  1448.6   492.6  1448.8   520.6 1453.07
   525.6 1455.39   560.6  1483.4   590.6 1500.51   610.6 1510.26   650.6  1533.8
   675.6 1549.96   685.6  1554.6   705.6 1568.55   730.6 1587.49   740.6 1596.29
   755.5 1606.77   805.5 1634.75   820.5 1640.57   865.5 1652.72   915.5 1662.56
#Mann= 3 , 0 , 0
       0      .1       0   477.6    .045       0   492.6      .1       0
Bank Sta=477.6,492.6
XS Rating Curve= 0 ,0
Exp/Cntr=0.3,0.1

Type RM Length L Ch R = 1 ,2684.2  ,122.4,122.6,122.9
XS GIS Cut Line= 2
     1782084.703      271019.357     1782540.312      271246.599
#Sta/Elev= 30
       0 1612.57      25 1602.64      30 1600.06    54.9 1584.75    94.8 1557.76
   104.8 1550.05   124.8 1533.17   129.8  1529.7   149.8 1518.79   189.7 1488.71
   204.6 1478.63   224.6 1467.66   249.6 1452.07   274.4 1440.85   279.5 1440.18
   289.4  1441.4   309.5 1447.35   314.5 1448.38   329.4 1449.61   334.4 1450.72
   354.4 1458.77   374.4 1463.72   389.3 1468.03   394.3 1470.05   414.3 1481.48
   434.3 1489.43   459.2 1504.72   479.2 1515.13   489.2 1516.38   509.1 1522.69
#Mann= 3 , 0 , 0
       0      .1       0   274.4    .045       0   289.4      .1       0
Bank Sta=274.4,289.4
XS Rating Curve= 0 ,0
Exp/Cntr=0.3,0.1

Type RM Length L Ch R = 1 ,2561.6  ,60.7,65.5,70.4
XS GIS Cut Line= 2
     1782070.078      271144.228     1782544.812      271381.595
#Sta/Elev= 30
       0 1585.07    29.8 1563.64    64.5 1537.13    94.2 1512.83    99.2 1509.25
   109.1 1505.31   114.1 1502.04     129 1488.85   143.8 1477.77   163.7 1460.41
   173.6  1454.2   193.5 1439.67   203.7 1436.03   208.3 1435.31   218.7 1436.24
   233.1 1439.99   262.9 1439.53   277.8 1443.48   302.6 1459.18   327.4 1479.43
   332.4 1482.13   357.2 1492.12     372 1500.12   401.8 1513.54   411.7 1519.22
   441.5 1531.68   466.3  1540.8   476.2 1545.79     506 1557.54   530.8 1568.76
#Mann= 3 , 0 , 0
       0      .1       0   203.7    .045       0   218.7      .1       0
Bank Sta=203.7,218.7
XS Rating Curve= 0 ,0
Exp/Cntr=0.3,0.1

Type RM Length L Ch R = 1 ,2496.1  ,224.8,217,209.3
XS GIS Cut Line= 2
     1782008.205      271162.227     1782381.693       271371.47
#Sta/Elev= 30
       0 1615.46    54.8 1578.08    79.6 1558.99    99.6 1544.59   114.5 1533.18
   129.4 1524.31   149.3 1506.74   164.3 1498.24   169.2 1494.83   184.2 1481.82
   189.2 1478.27   209.1 1466.64     224 1454.96   238.9 1442.14   243.9 1438.94
   248.9 1437.15   268.8 1434.03   278.9 1434.43   293.9 1433.47   308.6 1431.97
   318.6 1434.54   328.6 1438.19   338.5 1442.42   343.5 1445.26   358.4  1455.1
   368.4 1463.94   373.4 1467.81   383.3    1474   398.2 1484.99   428.1 1502.71
#Mann= 3 , 0 , 0
       0      .1       0   278.9    .045       0   293.9      .1       0
Bank Sta=278.9,293.9
XS Rating Curve= 0 ,0
Exp/Cntr=0.3,0.1

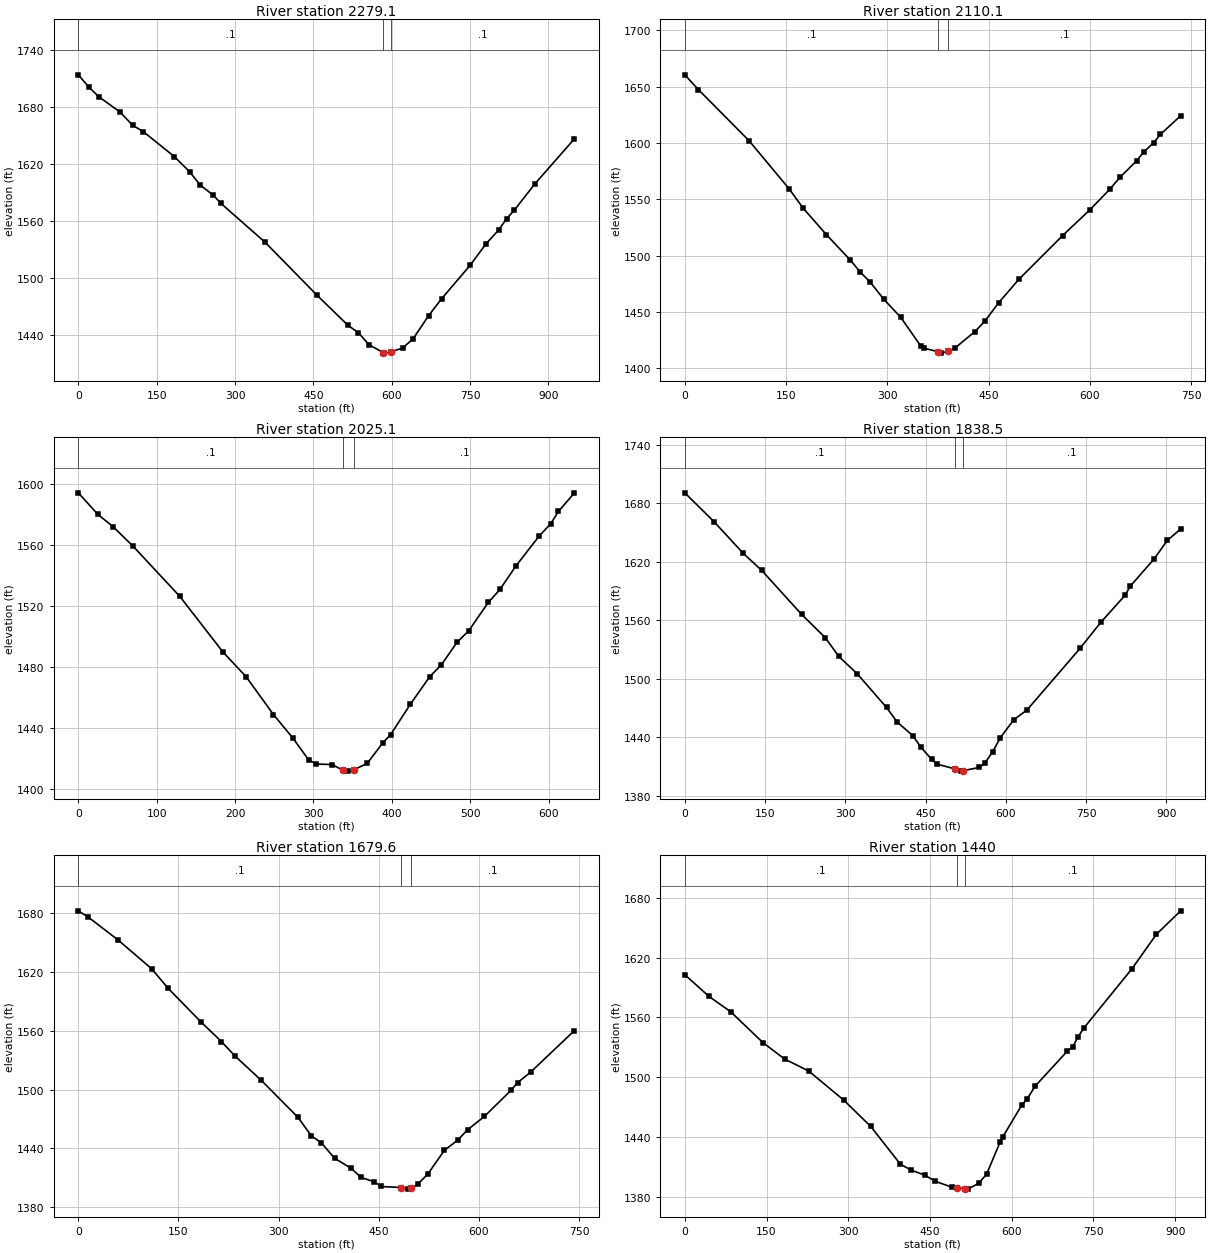
Type RM Length L Ch R = 1 ,2279.1  ,170.2,169,167.8
XS GIS Cut Line= 3
     1781660.313      271305.583      1782078.62      271462.024
     1782552.347      271629.858
#Sta/Elev= 30
       0 1713.62    19.8 1700.94    39.7 1690.39    79.4 1674.76   104.2 1660.53
   124.1 1654.08   183.6  1627.8   213.4 1611.58   233.2 1597.84     258 1587.36
   272.9 1578.61   357.3 1537.87   456.6 1482.28   516.3  1450.4   536.2 1442.76
   556.1 1430.26   583.9 1421.81   585.9 1421.28   598.9 1422.72   620.8 1426.71
   640.7 1436.21   670.5 1460.54   695.4 1478.38   750.1 1513.58     780  1535.8
   804.9 1550.79   819.8 1562.46   834.7  1571.5   874.5 1599.41   949.2 1646.06
#Mann= 3 , 0 , 0
       0      .1       0   583.9    .045       0   598.9      .1       0
Bank Sta=583.9,598.9
XS Rating Curve= 0 ,0
Exp/Cntr=0.3,0.1

Type RM Length L Ch R = 1 ,2110.1  ,85.7,85,84.2
XS GIS Cut Line= 2
     1781774.213      271550.027     1782478.189      271760.019
#Sta/Elev= 30
       0 1660.47      20 1647.45      95 1602.17   154.9 1559.12   174.9 1542.53
   209.9 1518.62   244.9 1496.37   259.9 1485.56   274.9 1476.43   294.8 1461.41
   319.8 1445.49   349.8 1419.75   354.8    1418   375.5  1414.8   379.8 1413.62
   390.5 1415.28   399.8 1417.93   429.8 1432.73   444.8 1442.14   464.8 1458.14
   494.8    1479   559.7 1517.85   599.7 1540.49   629.7    1559   644.7 1569.54
   669.7 1584.39   679.7 1591.84   694.6 1600.28   704.6 1607.56   734.6 1624.17
#Mann= 3 , 0 , 0
       0      .1       0   375.5    .045       0   390.5      .1       0
Bank Sta=375.5,390.5
XS Rating Curve= 0 ,0
Exp/Cntr=0.3,0.1

Type RM Length L Ch R = 1 ,2025.1  ,187.9,186.6,185.8
XS GIS Cut Line= 2
     1781794.213      271656.023     1782406.192      271816.017
#Sta/Elev= 30
       0 1594.53    24.9 1580.39    44.8 1572.06    69.7 1559.53   129.5 1526.48
   184.3  1490.1   214.2 1473.63     249 1448.85   273.9 1433.31   293.9 1419.08
   303.8 1416.34   323.8 1416.07   337.3  1412.3   343.7 1411.72   352.3 1412.75
   368.6 1416.85   388.5  1430.3   398.5 1435.73   423.4 1455.49   448.3 1473.76
   463.2 1481.56   483.1  1496.3   498.1 1503.92     523 1522.51   537.9 1531.03
   557.8 1546.17   587.7 1565.97   602.7 1574.28   612.6 1582.34   632.6 1594.29
#Mann= 3 , 0 , 0
       0      .1       0   337.3    .045       0   352.3      .1       0
Bank Sta=337.3,352.3
XS Rating Curve= 0 ,0
Exp/Cntr=0.3,0.1

Type RM Length L Ch R = 1 ,1838.5  ,166.5,158.9,150.8
XS GIS Cut Line= 3
     1781554.468      271875.119     1782004.969      271903.998
     1782471.381      271995.237
#Sta/Elev= 30
       0 1690.54    54.6 1660.94   109.1 1628.56   143.9 1610.89   218.3 1565.86
   262.9 1541.77   287.7 1522.81   322.4 1504.84     377 1470.41   396.9  1455.5
   426.6 1441.19   441.5 1429.44   461.3 1417.19   471.2 1412.29   505.1 1407.34
   515.8 1405.08   520.1  1405.5   550.4 1408.87   560.3 1412.95   575.2 1424.77
     590 1439.51   614.8 1457.74   639.6 1467.82   738.6 1530.93   778.2 1558.16
   822.7  1585.3   832.6  1594.8   877.2 1622.76   901.9 1641.75   926.7 1653.43
#Mann= 3 , 0 , 0
       0      .1       0   505.1    .045       0   520.1      .1       0
Bank Sta=505.1,520.1
XS Rating Curve= 0 ,0
Exp/Cntr=0.3,0.1

Type RM Length L Ch R = 1 ,1679.6  ,237.9,239.5,241.2
XS GIS Cut Line= 2
      1781586.22      272138.007     1782322.195       272038.01
#Sta/Elev= 30
       0 1682.69      15 1676.19    59.8 1652.75   109.7  1623.5   134.6  1603.4
   184.4 1568.57   214.4 1549.04   234.3 1534.47   274.2 1509.27     329 1471.54
   348.9 1452.77   363.9 1445.52   383.8 1429.72   408.8 1419.32   423.7 1410.05
   443.6 1405.54   453.6 1400.83   483.9 1399.79   493.5 1398.14   498.9 1398.87
   508.4 1403.19   523.4 1413.46   548.3  1437.8   568.3 1448.26   583.2 1458.94
   608.2 1472.43     648 1499.08     658    1507   677.9 1518.02   742.7 1559.98
#Mann= 3 , 0 , 0
       0      .1       0   483.9    .045       0   498.9      .1       0
Bank Sta=483.9,498.9
XS Rating Curve= 0 ,0
Exp/Cntr=0.3,0.1

Type RM Length L Ch R = 1 ,1440    ,146.7,143.2,139.6
XS GIS Cut Line= 3
     1781570.105      272341.163     1782024.309      272314.258
     1782478.513      272287.352
#Sta/Elev= 30
       0 1602.92    44.5 1581.06    84.1 1565.77   143.4 1534.73     183 1518.28
   227.5 1506.16   291.8 1476.95   341.2 1450.58   395.6  1412.7   415.4 1406.66
   440.2 1401.73     460 1395.38   489.6 1389.68   499.5 1389.19   514.5 1387.91
   519.3 1387.61   539.1 1393.28   553.9 1402.64   578.6 1434.79   583.6 1439.98
   618.2 1471.78   628.1 1477.92   642.9 1490.96   702.3 1526.33   712.2 1530.71
   722.1 1540.82     732 1549.12     821 1609.07   865.5 1643.45     910 1667.05
#Mann= 3 , 0 , 0
       0      .1       0   499.5    .045       0   514.5      .1       0
Bank Sta=499.5,514.5
XS Rating Curve= 0 ,0
Exp/Cntr=0.3,0.1

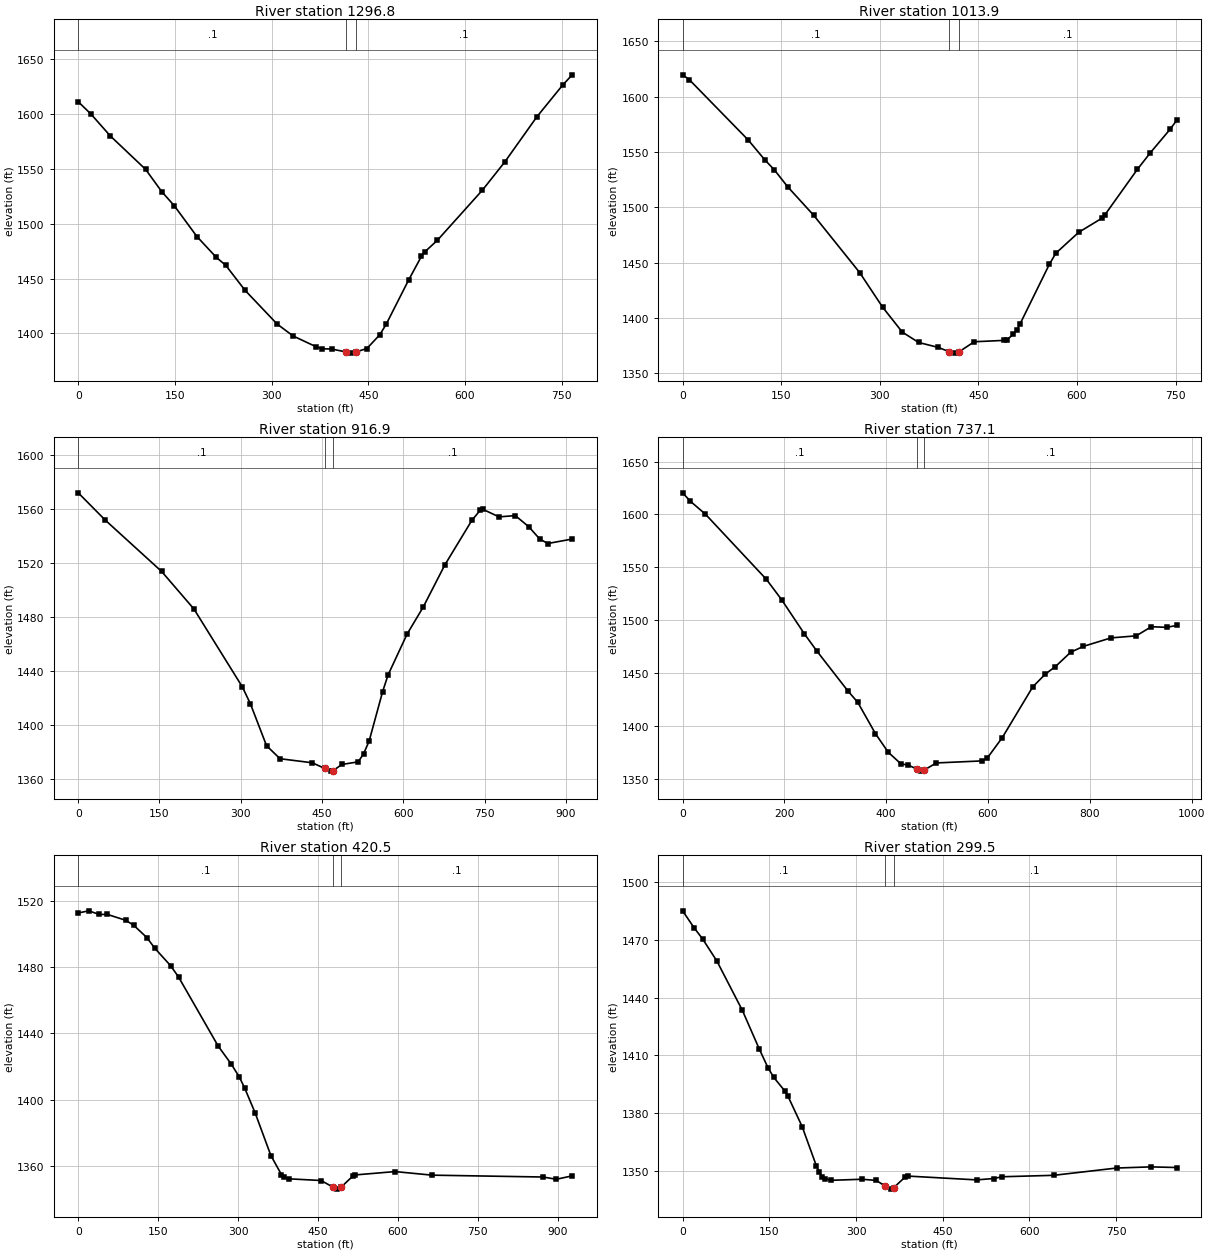
Type RM Length L Ch R = 1 ,1296.8  ,287.5,282.9,278
XS GIS Cut Line= 2
     1781676.217      272543.993     1782424.191      272377.999
#Sta/Elev= 30
       0 1610.89    19.9 1599.57    49.8 1579.73   104.5 1549.34   129.4 1529.18
   149.2 1516.08   184.1 1488.23   213.9 1469.43   228.9 1461.98   258.7 1439.32
   308.5  1408.6   333.3 1397.74   368.2 1388.15   378.1 1386.09     393 1385.87
   415.8 1383.14   422.9 1382.13   430.8 1383.22   447.8 1386.34   467.7  1398.8
   477.6 1408.32   512.4 1448.55   532.3 1470.16   537.3 1474.12   557.2 1484.89
   626.9 1530.39   661.7 1556.13   711.4 1597.16   751.2 1625.86   766.2 1635.37
#Mann= 3 , 0 , 0
       0      .1       0   415.8    .045       0   430.8      .1       0
Bank Sta=415.8,430.8
XS Rating Curve= 0 ,0
Exp/Cntr=0.3,0.1

Type RM Length L Ch R = 1 ,1013.9  ,90.5,97.1,101.9
XS GIS Cut Line= 3
     1781638.218      272737.986     1782022.205      272731.987
     1782360.193      272587.991
#Sta/Elev= 30
       0 1619.68      10 1615.38    99.8 1560.78   124.7 1543.09   139.6 1533.78
   159.6 1518.69   199.5 1492.69   269.3 1441.07   304.2 1409.81   334.2 1387.25
   359.1  1377.9     389 1373.43   405.7 1369.55   413.8 1368.29   420.7 1369.56
   443.6 1378.56   488.3 1379.78   493.3 1380.43   503.2 1385.27   508.2 1389.11
   513.1 1394.42   557.8 1448.44   567.7 1458.53   602.5 1477.42   637.2 1489.93
   642.2 1493.08   691.8 1534.33   711.7 1549.45   741.5 1570.45   751.4 1578.46
#Mann= 3 , 0 , 0
       0      .1       0   405.7    .045       0   420.7      .1       0
Bank Sta=405.7,420.7
XS Rating Curve= 0 ,0
Exp/Cntr=0.3,0.1

Type RM Length L Ch R = 1 ,916.9   ,182.4,179.8,179.3
XS GIS Cut Line= 3
     1781620.239      272869.486     1782073.429      272811.294
     1782515.418       272703.87
#Sta/Elev= 30
       0 1572.15    49.7 1551.96     154 1513.77   213.6 1485.92     303 1428.09
   317.8  1415.6   347.6 1384.49   372.5 1374.83   432.1 1371.81   454.8 1367.68
   466.9 1365.62   469.8 1365.84   486.9 1370.58   516.9 1372.51   526.9 1378.67
   536.9 1387.84   561.9 1424.64   571.9 1436.96   606.9 1467.22   636.8 1487.38
   676.8 1518.69   726.8 1551.85   741.8  1559.1   746.8 1559.91   776.8  1554.3
   806.8 1555.25   831.8 1546.94   851.8 1537.91   866.8 1534.54   911.8 1537.85
#Mann= 3 , 0 , 0
       0      .1       0   454.8    .045       0   469.8      .1       0
Bank Sta=454.8,469.8
XS Rating Curve= 0 ,0
Exp/Cntr=0.3,0.1

Type RM Length L Ch R = 1 ,737.1   ,318.7,316.6,311.4
XS GIS Cut Line= 3
     1781630.218      273105.974     1782276.196       272935.98
     1782522.188      272759.986
#Sta/Elev= 30
       0 1620.41      15  1612.5    44.9 1600.14   164.5 1538.58   194.4 1519.36
   239.3 1486.92   264.2  1470.4     324 1433.39     344 1422.24   378.8 1392.57
   403.8 1375.07   428.7 1364.06   443.6 1362.73   459.5 1359.23   468.6 1357.12
   474.5 1358.13   498.5 1364.87   588.2 1366.79   598.2 1369.28   628.1 1388.91
   687.8 1436.81   712.6 1448.95   732.4 1456.04   762.2 1469.55     787 1475.11
   841.5 1483.16   891.1 1485.11   920.8 1493.75   950.6 1493.15   970.4 1494.91
#Mann= 3 , 0 , 0
       0      .1       0   459.5    .045       0   474.5      .1       0
Bank Sta=459.5,474.5
XS Rating Curve= 0 ,0
Exp/Cntr=0.3,0.1

Type RM Length L Ch R = 1 ,420.5   ,113.9,120.9,131.2
XS GIS Cut Line= 3
     1781698.304      273401.949     1782160.794      273291.142
     1782558.976      273078.464
#Sta/Elev= 30
       0 1512.73    19.8 1514.02    39.6 1511.82    54.5 1511.87    89.2  1508.3
     104 1505.32   128.8 1497.88   143.7 1491.43   173.4  1480.9   188.2 1474.11
   262.6 1432.41   287.3 1421.47   302.2 1413.78   312.1 1407.26   331.9 1392.16
   361.6  1366.3   381.4 1354.83   386.4 1353.36   396.3 1352.27   455.8 1351.27
   478.4 1347.22   485.5 1346.07   493.4 1347.27   515.3 1353.95   520.2 1354.65
   594.6 1356.66   664.1  1354.5   872.4 1353.38   897.2 1352.02     927 1354.08
#Mann= 3 , 0 , 0
       0      .1       0   478.4    .045       0   493.4      .1       0
Bank Sta=478.4,493.4
XS Rating Curve= 0 ,0
Exp/Cntr=0.3,0.1

Type RM Length L Ch R = 1 ,299.5   ,215.2,215.1,215.1
XS GIS Cut Line= 4
     1781823.261      273391.997     1782103.472      273407.635
     1782331.225       273398.66     1782531.237      273116.007
#Sta/Elev= 30
       0 1485.13    19.7 1476.37    34.5 1470.55    59.1 1459.13   103.4 1433.39
   132.9 1413.16   147.7 1403.63   157.6 1398.63   177.2 1391.41   182.2 1388.87
   206.8 1373.06   231.4 1352.66   236.3 1349.33   241.3  1347.1   246.2 1346.07
     256 1345.12   310.4 1345.68   335.2 1345.06   350.3 1342.16   359.9 1340.55
   365.3  1341.3   384.7 1346.76   389.7 1347.33   508.6 1345.35   538.3 1346.06
   553.1 1346.98   642.1 1347.72     751 1351.51   810.3 1352.11   854.8 1351.78
#Mann= 3 , 0 , 0
       0      .1       0   350.3    .045       0   365.3      .1       0
Bank Sta=350.3,365.3
XS Rating Curve= 0 ,0
Exp/Cntr=0.3,0.1

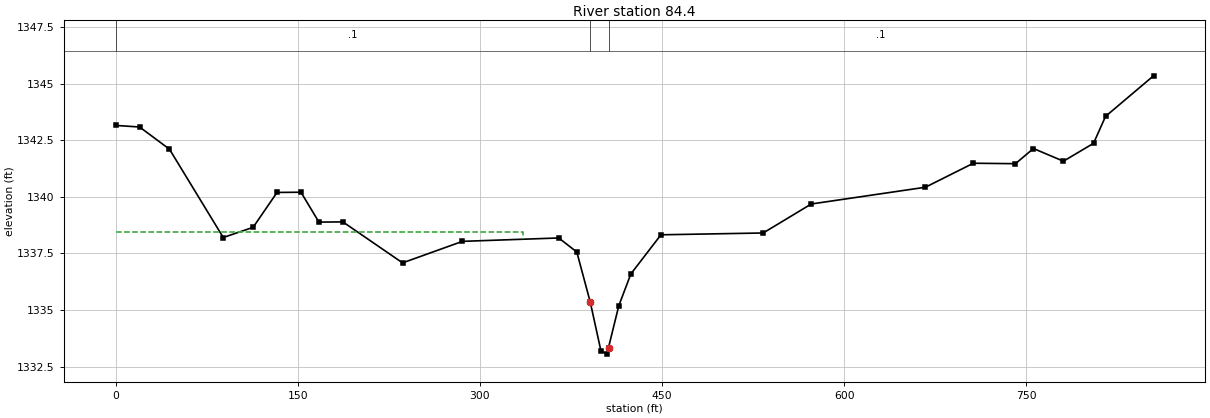
Type RM Length L Ch R = 1 ,84.4    ,91.5,84.4,77.3
XS GIS Cut Line= 4
     1781778.779       273604.13      1782058.99      273619.769
     1782286.743      273610.793     1782486.755       273328.14
#Sta/Elev= 30
       0 1343.15    19.7 1343.08    44.3  1342.1    88.6  1338.2   113.2 1338.65
   132.9 1340.19   152.6  1340.2   167.4 1338.88   187.1 1338.89   236.3 1337.08
   285.6 1338.03   364.9 1338.18   379.8 1337.56   390.9 1335.34   399.6 1333.21
   404.5 1333.05   405.9 1333.34   414.4 1335.19   424.3 1336.59   449.1 1338.32
   533.3  1338.4   572.9 1339.68   666.9 1340.42   706.4 1341.48   741.1 1341.46
   755.9 1342.13   780.6 1341.57   805.4 1342.36   815.3 1343.55   854.8 1345.34
#Mann= 3 , 0 , 0
       0      .1       0   390.9    .045       0   405.9      .1       0
#XS Ineff= 2 , 0
           335.7 1338.45
Permanent Ineff=
       F       F
Bank Sta=390.9,405.9
XS Rating Curve= 0 ,0
Exp/Cntr=0.3,0.1

Chan Stop Cuts=-1
Use User Specified Reach Order=0